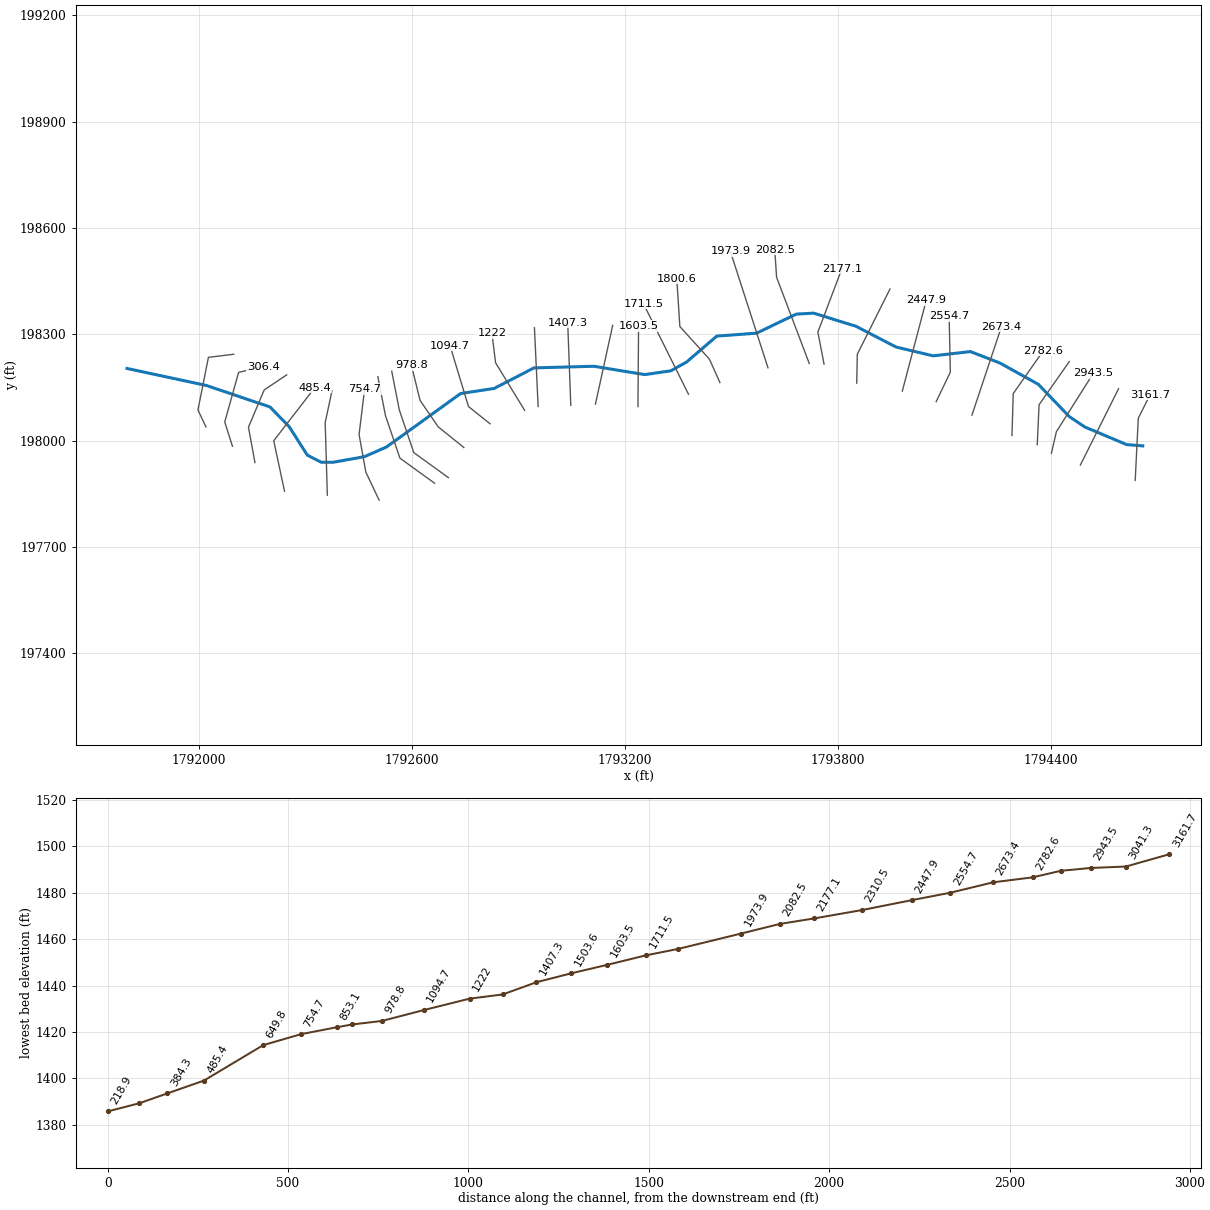
--- ISLANDRN.prj (project) ---

Proj Title=ISLANDRN
Current Plan=p01
Default Exp/Contr=0,0
English Units
Geom File=g01
Flow File=f01
Plan File=p01
BEGIN DESCRIPTION:
END DESCRIPTION:
DSS Export Rating Curves= 0
DSS Export Rating Curve Sorted= 0
DSS Export Volume Flow Curves= 0
DXF OffsetX= 0
DXF OffsetY= 0
DXF ScaleX= 0
DXF ScaleY= 0

--- ISLANDRN.p01 (plan) ---

Plan Title=Floodplain
Program Version=4.00
Geom File=g01
Flow File=f01
K Sum by GR=0
Std Step Tol=0.01
Critical Tol=0.01
Num of Std Step Trials=20
Max Error Tol=0.3
Flow Tol Ratio=0.001
Split Flow NTrial=30
Split Flow Tol=0.02
Split Flow Ratio=0.02
Log Output Level=0
Friction Slope Method=1
Unsteady Friction Slope Method=2
Unsteady Bridges Friction Slope Method=1
Global Log Level=0
CheckData=False
Run HTab=0
Run UNet=0
Run PostProcess=0
UNET Theta=0
UNET Theta Warmup=0
UNET ZTol=0
UNET ZSATol=0
UNET MxIter=0
UNET MaxInSteps=0
UNET DtIC=0
UNET DtMin=0
UNET MaxCRTS=0
UNET WFStab=0
UNET SFStab=0
UNET WFX=0
UNET SFX=0
UNET DSS MLevel=0
UNET DZMax Abort=0
UNET Convert EG Bridges=0
UNET Use Existing IB Tables=0
UNET Froude Limit=0
UNET Froude Power=0
Write IC File=0
Echo Input=False
Echo Output=False
Write Detailed=0

--- ISLANDRN.f01 (steady flow) ---

Flow Title=NFF Regression Equation
Program Version=4.00
Number of Profiles=1
Profile Names=P100yr
River Rch & RM=ISLANDRN,Main      ,3161.7
504.5963
River Rch & RM=ISLANDRN,Main      ,2673.4
540.3102
River Rch & RM=ISLANDRN,Main      ,485.4
581.4365
River Rch & RM=ISLANDRN,Main      ,218.9
582.4808
Boundary for River Rch & Prof#=ISLANDRN,Main      ,1
Up Type=0
Dn Type=3
Dn Slope=0.049691

--- ISLANDRN.g01 (geometry) ---

Geom Title=USGS 10m DEM
Program Version=4.10

River Reach=ISLANDRN        ,Main
Reach XY= 30
      1794658.57      197984.969     1794612.916      197988.686
     1794495.543      198038.191     1794452.128      198067.168
     1794364.051      198158.835     1794256.041      198218.732
      1794173.09      198250.983     1794068.067      198238.909
     1793963.664      198263.692     1793850.641      198322.313
     1793731.209      198359.409     1793682.287       198356.65
     1793570.438      198302.873     1793458.459       198294.67
     1793373.228      198221.376     1793328.798      198196.712
     1793255.449      198186.033     1793112.001      198209.544
      1792943.35      198204.948     1792831.318      198147.047
     1792736.578      198132.586      1792528.04      197982.037
      1792465.98      197954.549     1792377.911      197938.786
     1792343.879       197938.79     1792304.738      197958.846
     1792253.565      198039.228     1792199.367      198094.817
     1792020.466      198155.337     1791796.839      198203.315

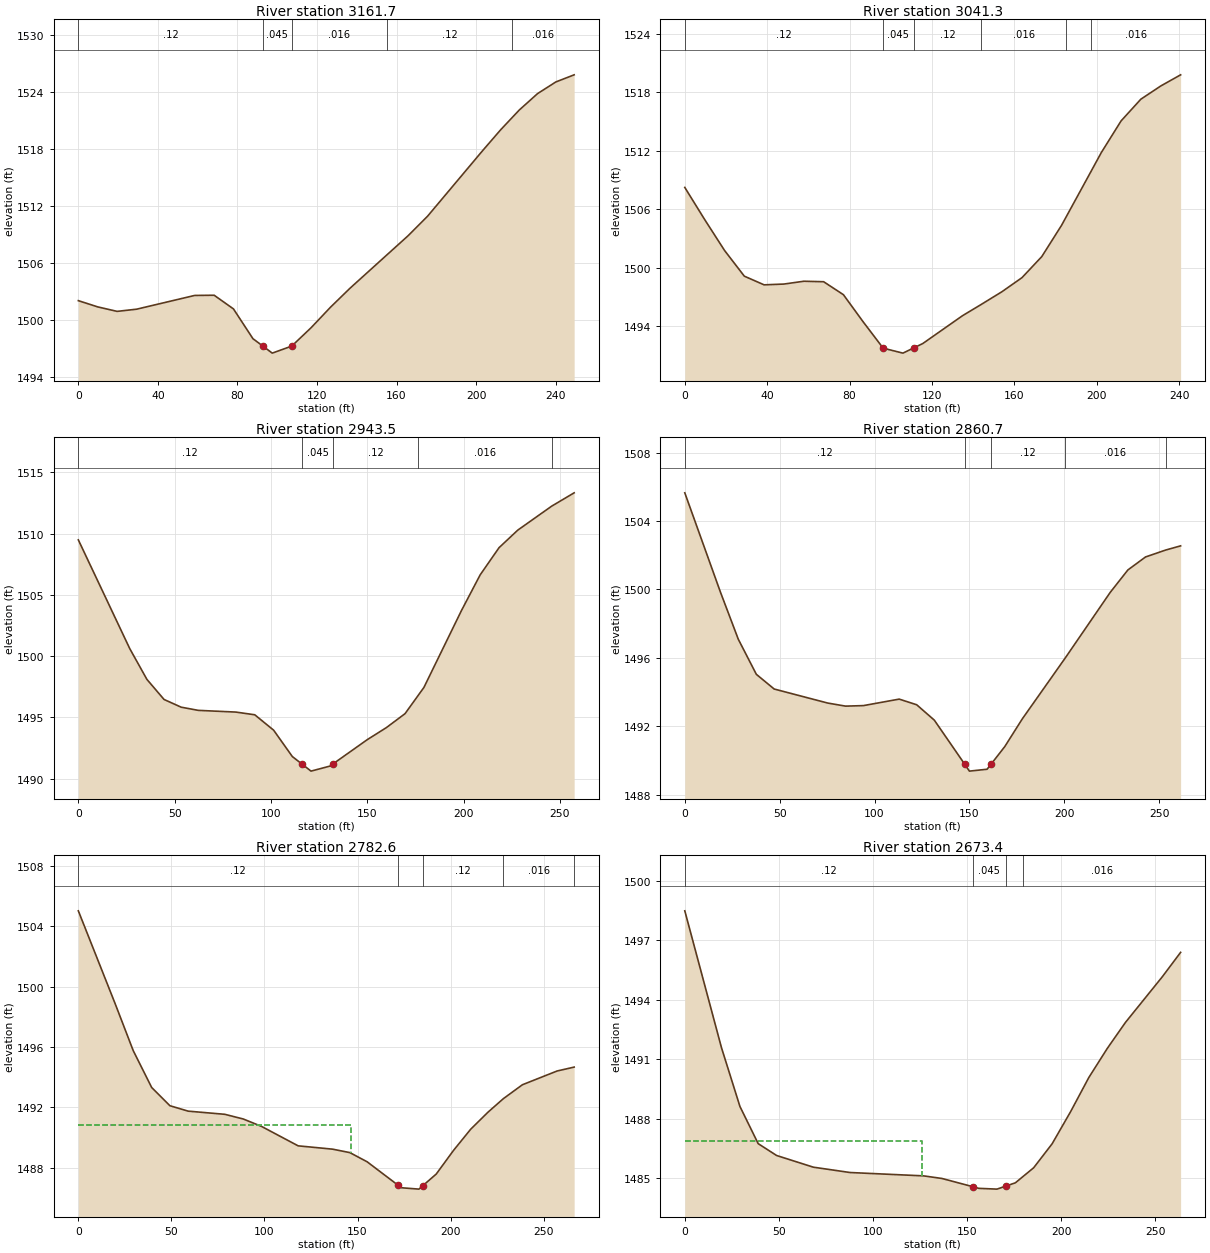
Type RM Length L Ch R = 1 ,3161.7  ,129.8,120.4,111.1
XS GIS Cut Line= 3
     1794637.342      197887.565     1794646.023      198062.913
     1794679.009      198128.885
#Sta/Elev= 24
       0 1502.05     9.8 1501.39    19.5 1500.92    29.3 1501.15    58.5  1502.6
    68.3 1502.62      78 1501.18    87.8 1498.04   92.831497.255    97.5 1496.52
   107.3 1497.26     117 1499.19   126.8 1501.36   136.6 1503.36  155.181506.879
   165.8 1508.89   175.6 1510.95   203.2 1517.84   212.4 1520.07   218.21521.361
   221.7 1522.14   230.9 1523.87   240.1  1525.1   249.3 1525.85
#Mann= 5 ,-1 , 0
       0     .12       0   92.83    .045       0   107.3    .016       0
  155.18     .12       0   218.2    .016       0
Bank Sta=92.83,107.3
XS Rating Curve= 0 ,0
Exp/Cntr=0.3,0.1

Type RM Length L Ch R = 1 ,3041.3  ,99.9,97.8,95.7
XS GIS Cut Line= 2
     1794482.828      197930.968     1794590.467      198146.246
#Sta/Elev= 27
       0 1508.24     9.6 1504.96    19.3 1501.77    28.9 1499.13    38.5 1498.24
    48.1 1498.32    57.8 1498.61    67.4 1498.56      77 1497.23    86.6 1494.44
    96.3 1491.74   105.9 1491.23  111.111491.764   115.5 1492.21   134.8 1495.07
  143.831496.218     154 1497.54   163.7 1498.98   173.3 1501.14   182.9 1504.35
  185.091505.197  196.951509.786   202.2 1511.82   211.8 1515.07   221.4  1517.3
   231.1 1518.66   240.7  1519.8
#Mann= 6 ,-1 , 0
       0     .12       0    96.3    .045       0  111.11     .12       0
  143.83    .016       0  185.09     .12       0  196.95    .016       0
Bank Sta=96.3,111.11
XS Rating Curve= 0 ,0
Exp/Cntr=0.3,0.1

Type RM Length L Ch R = 1 ,2943.5  ,84.1,82.8,81.6
XS GIS Cut Line= 3
     1794401.231      197963.954      1794415.12      198024.718
     1794519.286      198189.649
#Sta/Elev= 25
       0 1509.49    26.7 1500.61    35.6  1498.1    44.5 1496.46    53.4 1495.83
    62.3 1495.57    81.8 1495.43    91.6 1495.21   101.4 1493.95   111.1  1491.8
  116.121491.186   120.8 1490.61   130.6 1491.02  132.191491.197   150.1 1493.19
   159.9 1494.16   169.6  1495.3  176.441496.794   179.4 1497.44   198.9 1503.72
   208.6 1506.63   218.4 1508.85   228.1 1510.28  245.721512.241   257.4 1513.33
#Mann= 5 ,-1 , 0
       0     .12       0  116.12    .045       0  132.19     .12       0
  176.44    .016       0  245.72     .12       0
Bank Sta=116.12,132.19
XS Rating Curve= 0 ,0
Exp/Cntr=0.3,0.1

Type RM Length L Ch R = 1 ,2860.7  ,78.1,78.1,78.1
XS GIS Cut Line= 3
       1794361.3       197988.26     1794366.509      198101.107
     1794451.578      198222.635
#Sta/Elev= 23
       0 1505.65    18.8 1499.84    28.2 1497.09    37.7 1495.04    47.1 1494.18
    75.3 1493.36    84.7 1493.18    94.1 1493.21     113 1493.59   122.2 1493.26
   131.5 1492.36   147.51489.787     150 1489.38   159.3 1489.49   161.5  1489.8
   168.6 1490.81   177.9 1492.44  200.431495.984   224.2 1499.83   233.5 1501.14
   242.8  1501.9  253.371502.303   261.3 1502.55
#Mann= 5 ,-1 , 0
       0     .12       0   147.5    .045       0   161.5     .12       0
  200.43    .016       0  253.37     .12       0
Bank Sta=147.5,161.5
XS Rating Curve= 0 ,0
Exp/Cntr=0.3,0.1

Type RM Length L Ch R = 1 ,2782.6  ,102.7,109.2,115.7
XS GIS Cut Line= 3
      1794290.12      198014.301     1794293.592      198132.357
     1794378.661      198253.885
#Sta/Elev= 26
       0 1505.02    19.7 1498.89    29.5 1495.75    39.4 1493.31    49.2  1492.1
      59 1491.74    78.7 1491.53    88.6 1491.22    98.4 1490.73   118.1 1489.44
   136.6 1489.22   145.9 1488.99   155.2 1488.38   171.61486.847   173.7 1486.66
     183 1486.57   185.1  1486.8   192.3 1487.57   201.6 1489.14   210.8 1490.54
   220.1 1491.67  228.341492.565   238.6 1493.49   257.2  1494.4  266.341494.658
   266.4 1494.66
#Mann= 5 ,-1 , 0
       0     .12       0   171.6    .045       0   185.1     .12       0
  228.34    .016       0  266.34     .12       0
#XS Ineff= 2 , 0
          146.75 1490.83
Permanent Ineff=
       F       F
Bank Sta=171.6,185.1
XS Rating Curve= 0 ,0
Exp/Cntr=0.3,0.1

Type RM Length L Ch R = 1 ,2673.4  ,110.8,118.7,126.6
XS GIS Cut Line= 2
     1794177.273      198071.593     1794260.606      198321.593
#Sta/Elev= 23
       0  1498.5    19.5 1491.58    29.3 1488.61      39 1486.73    48.8 1486.13
    68.3 1485.54    87.8 1485.27   126.9  1485.1   136.6 1484.97  152.921484.557
   156.2 1484.47   165.9 1484.43  170.761484.588   175.7 1484.75   179.51485.048
   185.4 1485.51   195.2 1486.72     205 1488.34   214.7 1490.07   224.5 1491.54
   234.2 1492.86   253.8 1495.17   263.5  1496.4
#Mann= 4 ,-1 , 0
       0     .12       0  152.92    .045       0  170.76     .12       0
   179.5    .016       0
#XS Ineff= 2 , 0
          126.32 1486.86
Permanent Ineff=
       F       F
Bank Sta=152.92,170.76
XS Rating Curve= 0 ,0
Exp/Cntr=0.3,0.1

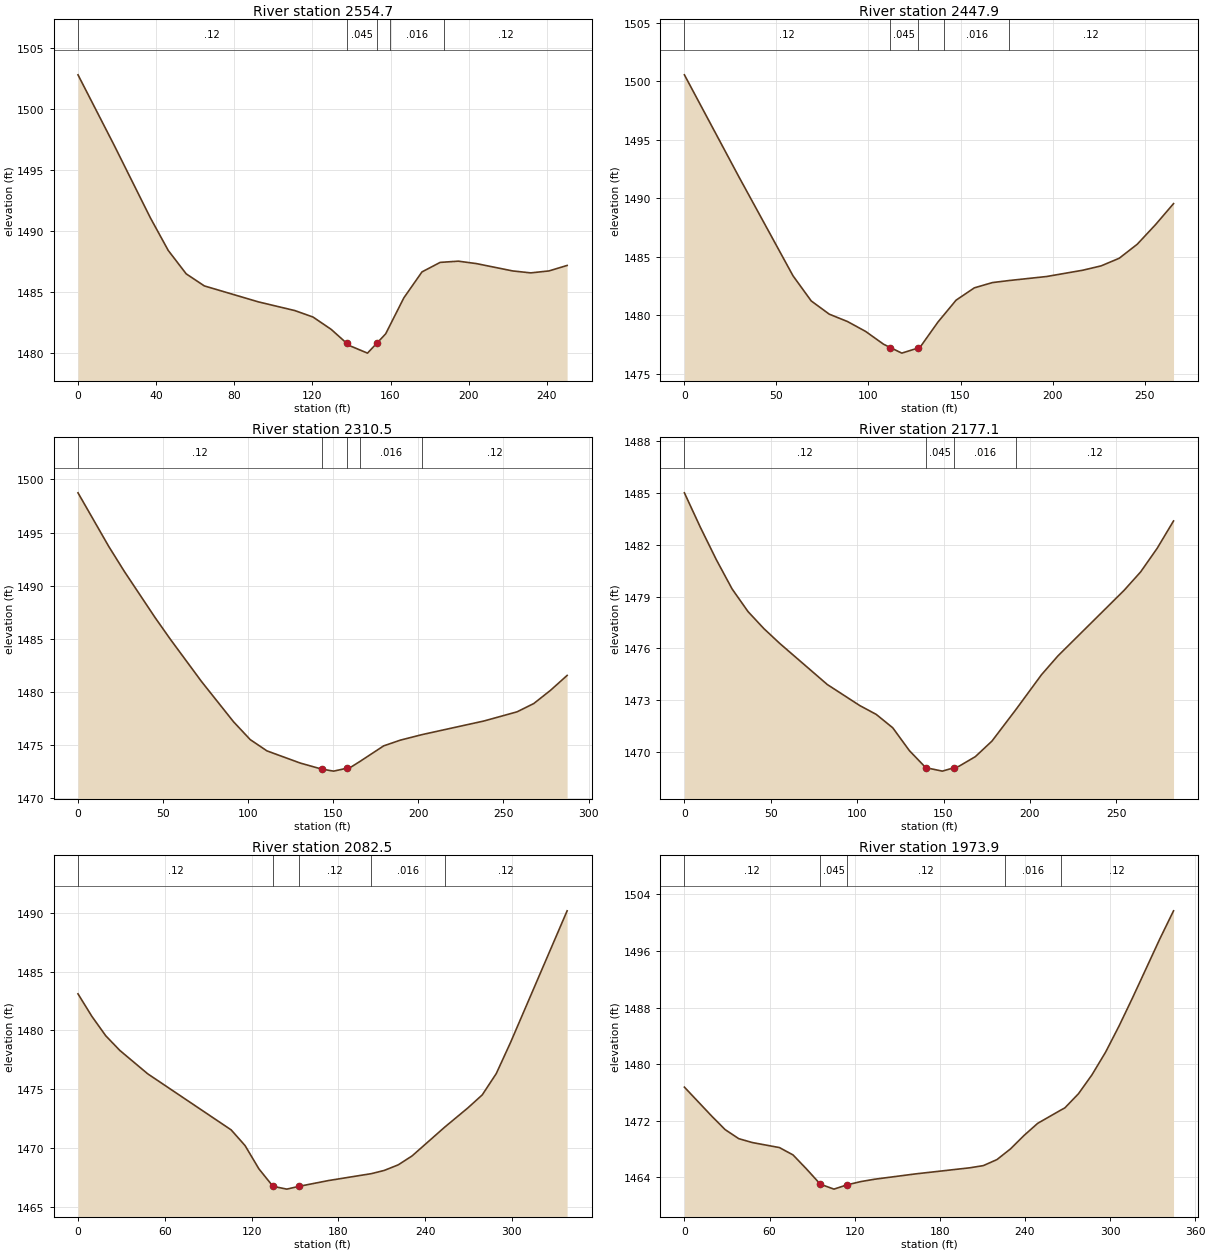
Type RM Length L Ch R = 1 ,2554.7  ,113.1,106.7,100.2
XS GIS Cut Line= 3
     1794076.578      198109.788     1794116.509      198193.121
     1794113.036      198351.107
#Sta/Elev= 26
       0 1502.78    18.5 1497.01      37 1491.07    46.2 1488.38    55.4 1486.46
    64.7 1485.47    92.4 1484.16     111 1483.45   120.3 1482.92   129.6 1481.91
  137.531480.772   138.8 1480.59   148.2 1479.96  153.131480.796   157.5 1481.54
  159.811482.273   166.8 1484.49   176.1 1486.62   185.4  1487.4  187.441487.422
   194.7  1487.5     204  1487.3   222.5  1486.7   231.8 1486.54   241.1  1486.7
   250.4 1487.15
#Mann= 5 ,-1 , 0
       0     .12       0  137.53    .045       0  153.13     .12       0
  159.81    .016       0  187.44     .12       0
Bank Sta=137.53,153.13
XS Rating Curve= 0 ,0
Exp/Cntr=0.3,0.1

Type RM Length L Ch R = 1 ,2447.9  ,142.1,137.5,132.7
XS GIS Cut Line= 2
     1793981.092      198139.301       1794048.8      198396.246
#Sta/Elev= 25
       0 1500.55    29.5 1491.86      59 1483.37    68.9 1481.22    78.7 1480.09
    88.6 1479.46    98.4 1478.62   108.2 1477.52   111.8 1477.24   118.1 1476.76
   126.8 1477.19   127.9 1477.24   137.8 1479.43   141.21480.075   147.6 1481.29
   157.5 1482.34   167.3 1482.79  176.351482.965   196.8 1483.31   216.5 1483.85
   226.4 1484.22   236.2 1484.87     246 1486.07   255.9 1487.74   265.7 1489.54
#Mann= 5 ,-1 , 0
       0     .12       0   111.8    .045       0   126.8     .12       0
   141.2    .016       0  176.35     .12       0
Bank Sta=111.8,126.8
XS Rating Curve= 0 ,0
Exp/Cntr=0.3,0.1

Type RM Length L Ch R = 1 ,2310.5  ,131.1,133.4,135.7
XS GIS Cut Line= 3
      1793852.62      198161.871     1793854.356      198243.468
      1793946.37      198427.496
#Sta/Elev= 23
       0 1498.74    18.1 1493.68    27.2 1491.34    45.3 1486.98    54.4 1484.91
    72.6 1480.95    91.4 1477.16   101.2 1475.48     111 1474.42   130.6 1473.27
   143.2  1472.7   150.2 1472.51   158.2 1472.79     160 1472.85  165.861473.442
   179.6 1474.89   189.4 1475.43   202.31475.957   238.4 1477.23     258  1478.1
   267.8 1478.88   277.6 1480.12   287.4 1481.53
#Mann= 5 ,-1 , 0
       0     .12       0   143.2    .045       0   158.2     .12       0
  165.86    .016       0   202.3     .12       0
Bank Sta=143.2,158.2
XS Rating Curve= 0 ,0
Exp/Cntr=0.3,0.1

Type RM Length L Ch R = 1 ,2177.1  ,78.1,94.6,110.8
XS GIS Cut Line= 3
     1793760.606       198215.69     1793743.245      198305.968
     1793810.953      198484.788
#Sta/Elev= 25
       0 1485.02     9.2 1483.03    18.4 1481.16    27.6 1479.45    36.8 1478.14
      46 1477.15    55.2 1476.29    82.7 1473.91   101.5 1472.69     111 1472.18
   120.6  1471.4   130.2 1470.08   139.7 1469.09   149.3 1468.89  156.17 1469.09
   158.9 1469.17   168.4 1469.73     178 1470.63  191.751472.442   206.7 1474.48
   216.2 1475.57   254.5 1479.37     264 1480.43   273.6  1481.8   283.1 1483.39
#Mann= 4 ,-1 , 0
       0     .12       0   139.7    .045       0  156.17    .016       0
  191.75     .12       0
Bank Sta=139.7,156.17
XS Rating Curve= 0 ,0
Exp/Cntr=0.3,0.1

Type RM Length L Ch R = 1 ,2082.5  ,109.7,108.6,107.4
XS GIS Cut Line= 3
     1793718.939      198217.426     1793626.925      198460.482
     1793621.717      198538.607
#Sta/Elev= 22
       0 1483.11     9.6  1481.2    19.2 1479.55    28.9 1478.31    48.1 1476.33
   105.9 1471.56   115.5 1470.23   125.1 1468.25   134.8 1466.77   144.4 1466.53
  152.571466.761   173.3 1467.26  202.931467.846   211.8 1468.12   221.4 1468.59
     231 1469.35  253.471471.784   269.7 1473.44   279.5 1474.53   289.2 1476.34
     299 1478.96   338.2 1490.16
#Mann= 5 ,-1 , 0
       0     .12       0   134.8    .045       0  152.57     .12       0
  202.93    .016       0  253.47     .12       0
Bank Sta=134.8,152.57
XS Rating Curve= 0 ,0
Exp/Cntr=0.3,0.1

Type RM Length L Ch R = 1 ,1973.9  ,163.2,173.2,182.4
XS GIS Cut Line= 2
      1793602.62      198205.274     1793496.717      198533.399
#Sta/Elev= 30
       0 1476.76    19.2 1472.68    28.7 1470.76    38.3 1469.48    47.9 1468.93
      67 1468.22    76.6 1467.18    86.2 1465.17    95.8 1463.05   105.4 1462.35
   114.9 1462.97   124.5 1463.42   134.1 1463.75   162.8  1464.5   201.1 1465.36
   210.7 1465.67   220.3 1466.52  226.061467.432   229.9 1468.04   239.4 1469.93
     249 1471.64  265.241473.506   268.2 1473.83   277.8 1475.83   287.3  1478.5
   296.9  1481.7   306.5 1485.44   316.1 1489.46   335.2 1497.73   344.8 1501.67
#Mann= 5 ,-1 , 0
       0     .12       0    95.8    .045       0   114.9     .12       0
  226.06    .016       0  265.24     .12       0
Bank Sta=95.8,114.9
XS Rating Curve= 0 ,0
Exp/Cntr=0.3,0.1

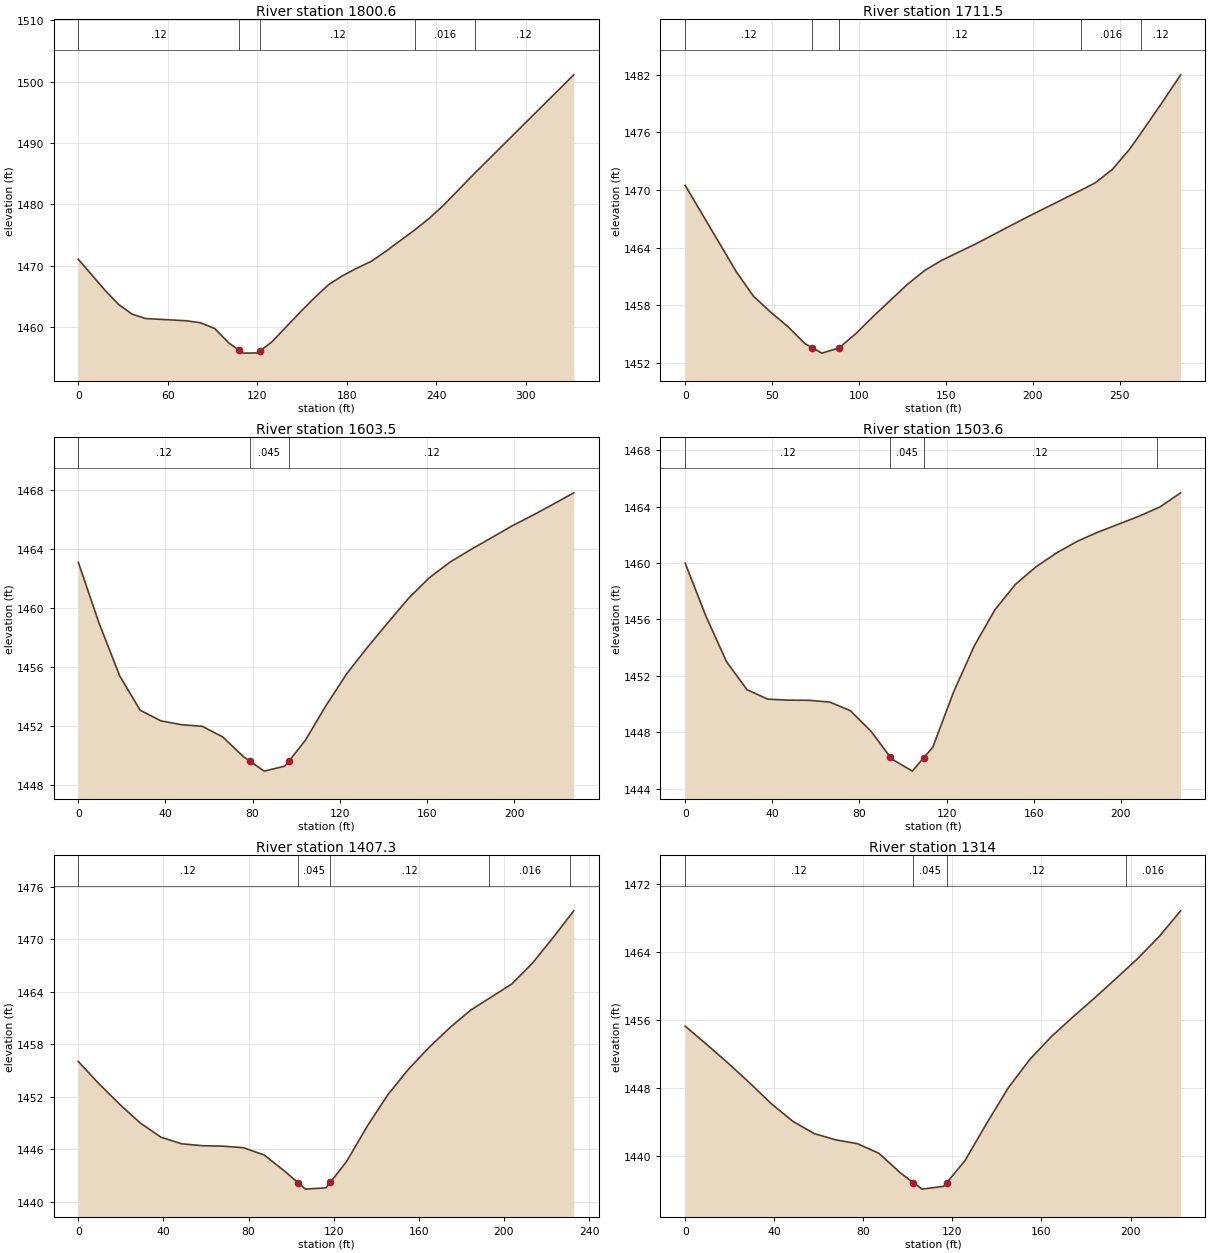
Type RM Length L Ch R = 1 ,1800.6  ,95.4,89.2,82.9
XS GIS Cut Line= 4
     1793467.203      198163.607     1793437.689      198229.579
     1793354.356      198321.593     1793345.675       198457.01
#Sta/Elev= 26
       0 1471.06    18.1 1465.96    27.1  1463.7    36.1 1462.12    45.2 1461.41
    72.3 1461.05    81.8 1460.73    91.4 1459.79   100.9 1457.44  107.931456.224
   110.5 1455.78     120 1455.81  121.941456.168   129.6 1457.58   148.7 1462.44
   158.2 1464.77   167.8 1466.93   177.3 1468.41   186.9 1469.63   196.4 1470.73
   206.1 1472.35  225.461475.833   235.2 1477.72   244.9 1479.87  265.621485.051
   332.1 1501.09
#Mann= 5 ,-1 , 0
       0     .12       0  107.93    .045       0  121.94     .12       0
  225.46    .016       0  265.62     .12       0
Bank Sta=107.93,121.94
XS Rating Curve= 0 ,0
Exp/Cntr=0.3,0.1

Type RM Length L Ch R = 1 ,1711.5  ,118.6,108,97.3
XS GIS Cut Line= 2
     1793378.661      198130.621     1793251.925      198385.829
#Sta/Elev= 23
       0 1470.48    29.5 1461.46    39.3 1458.93    49.1 1457.29      59 1455.78
    68.8 1454.01   73.141453.569    78.6 1453.01    88.4 1453.54    98.3 1455.07
   108.1 1456.83   127.7 1460.16   137.6 1461.61   147.4 1462.67     167 1464.38
   196.5 1467.17  227.871470.005   235.8 1470.75   245.6 1472.14   255.5 1474.24
  262.151475.943   275.1 1479.34   284.9    1482
#Mann= 5 ,-1 , 0
       0     .12       0   73.14    .045       0    88.4     .12       0
  227.87    .016       0  262.15     .12       0
Bank Sta=73.14,88.4
XS Rating Curve= 0 ,0
Exp/Cntr=0.3,0.1

Type RM Length L Ch R = 1 ,1603.5  ,104.6,99.9,95.2
XS GIS Cut Line= 2
       1793236.3      198095.899     1793238.036      198323.329
#Sta/Elev= 29
       0 1463.08     9.5 1458.96      19 1455.37    28.4 1453.04    37.9 1452.32
    47.4 1452.06    56.9 1451.95    66.3 1451.23    75.8 1449.89   78.661449.594
    84.6 1448.98    85.3 1448.91    94.8 1449.25   96.781449.617    99.6 1450.14
   104.2    1451   113.7 1453.36   123.2 1455.52   132.7 1457.31   142.2    1459
   151.6 1460.64   161.1 1462.03   170.6 1463.09     180 1463.93   189.5 1464.73
     199 1465.54   208.5 1466.26     218 1467.02   227.4 1467.79
#Mann= 3 ,-1 , 0
       0     .12       0   78.66    .045       0   96.78     .12       0
Bank Sta=78.66,96.78
XS Rating Curve= 0 ,0
Exp/Cntr=0.3,0.1

Type RM Length L Ch R = 1 ,1503.6  ,90.6,96.3,102
XS GIS Cut Line= 2
     1793116.509      198102.843      1793165.12      198325.065
#Sta/Elev= 30
       0 1459.99     9.5 1456.24      19    1453    28.4 1451.02    37.9 1450.35
    47.4 1450.28    56.9 1450.27    66.4 1450.14    75.8 1449.54    85.3 1448.08
    94.11446.264    94.8 1446.12    95.2 1446.08   104.3 1445.25  109.611446.213
   110.2 1446.32   113.7 1446.95   123.2 1450.84   132.7 1454.11   142.2 1456.68
   151.6 1458.48   161.1 1459.73   170.6 1460.72   180.1 1461.54   189.6 1462.19
     199 1462.75   208.5 1463.32  216.471463.865     218 1463.97   227.5 1464.97
#Mann= 4 ,-1 , 0
       0     .12       0    94.1    .045       0  109.61     .12       0
  216.47    .016       0
Bank Sta=94.1,109.61
XS Rating Curve= 0 ,0
Exp/Cntr=0.3,0.1

Type RM Length L Ch R = 1 ,1407.3  ,93.1,93.4,93.6
XS GIS Cut Line= 2
     1793047.064      198099.371     1793038.384       198332.01
#Sta/Elev= 29
       0 1456.03     9.7 1453.48    19.4 1451.14    29.1 1448.99    38.8 1447.37
    48.5 1446.61    58.2 1446.39    67.9 1446.34    77.6 1446.16    87.3 1445.33
      97 1443.47   103.4 1442.12   106.7 1441.42   116.4 1441.57   118.4 1442.19
   126.1  1444.6   135.8 1448.64   145.5 1452.24   155.2 1455.16   164.9 1457.66
   174.6  1459.9   184.3  1461.9  193.191463.275     194  1463.4   203.7  1464.9
   213.4 1467.29   223.1 1470.21  231.081472.727   232.8 1473.27
#Mann= 5 ,-1 , 0
       0     .12       0   103.4    .045       0   118.4     .12       0
  193.19    .016       0  231.08     .12       0
Bank Sta=103.4,118.4
XS Rating Curve= 0 ,0
Exp/Cntr=0.3,0.1

Type RM Length L Ch R = 1 ,1314    ,80.6,91.9,103.2
XS GIS Cut Line= 2
      1792955.05      198095.899     1792944.634      198318.121
#Sta/Elev= 27
       0 1455.32     9.7 1453.16    19.3 1450.97      29 1448.64    38.7  1446.2
    48.4 1444.12      58 1442.68    67.7 1441.95    77.4  1441.5      87 1440.37
    96.7 1438.06   102.5 1436.92   106.4 1436.16   116.1 1436.49   117.5 1436.93
   125.7 1439.53   135.4  1443.9   145.1 1448.07   154.8 1451.42   164.4 1454.08
   174.1  1456.4   183.8 1458.62   193.4  1460.9  197.941461.995   203.1 1463.24
   212.8 1465.84   222.5 1468.88
#Mann= 4 ,-1 , 0
       0     .12       0   102.5    .045       0   117.5     .12       0
  197.94    .016       0
Bank Sta=102.5,117.5
XS Rating Curve= 0 ,0
Exp/Cntr=0.3,0.1

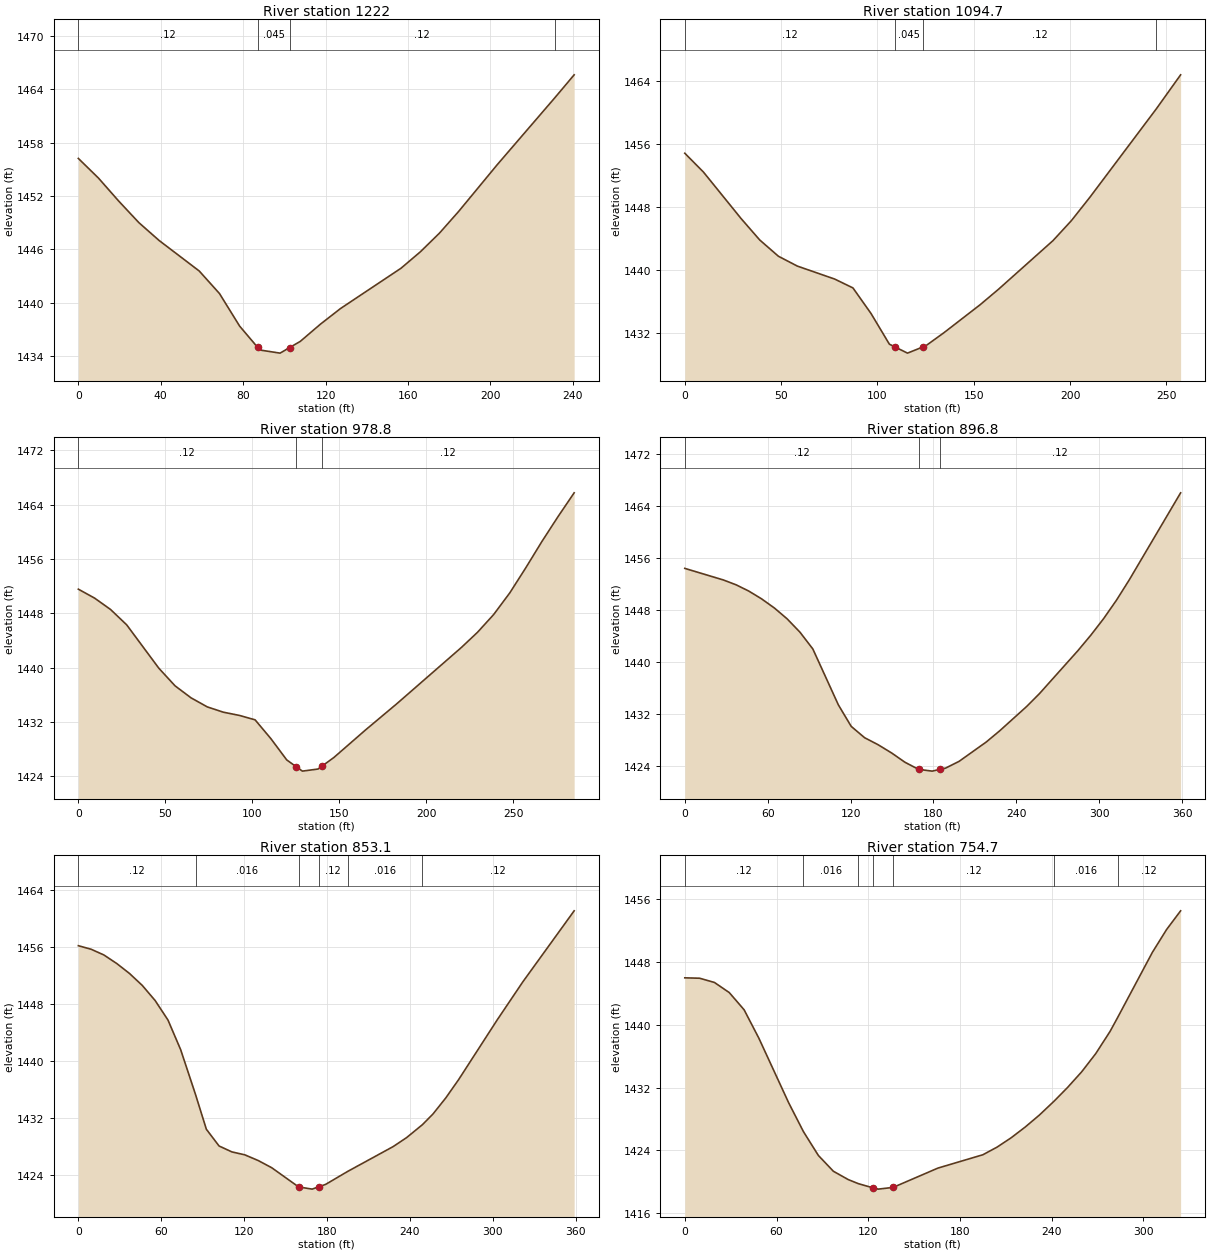
Type RM Length L Ch R = 1 ,1222    ,133.1,127.4,121.6
XS GIS Cut Line= 3
     1792916.856      198085.482     1792835.259      198219.163
     1792824.842      198302.496
#Sta/Elev= 22
       0 1456.24     9.8 1454.02    19.6 1451.44    29.4 1449.01    39.2 1447.01
    58.7 1443.57    68.5 1441.04    78.3 1437.37   87.01 1434.99    88.1 1434.69
    97.9 1434.34  102.571434.971   107.7 1435.66   117.5  1437.6   127.2 1439.35
   156.6 1443.89     166 1445.74   175.3 1447.85   184.6 1450.29   203.3 1455.54
  231.111463.029   240.6 1465.64
#Mann= 4 ,-1 , 0
       0     .12       0   87.01    .045       0  102.57     .12       0
  231.11    .016       0
Bank Sta=87.01,102.57
XS Rating Curve= 0 ,0
Exp/Cntr=0.3,0.1

Type RM Length L Ch R = 1 ,1094.7  ,108.9,115.9,122.9
XS GIS Cut Line= 3
     1792819.634      198047.288      1792758.87      198095.899
     1792706.786      198267.774
#Sta/Elev= 22
       0 1454.84     9.7 1452.44    29.2 1446.54    38.9 1443.81    48.6 1441.74
    58.4 1440.49    77.8 1438.84    87.3 1437.71    96.7 1434.45   106.2 1430.56
  108.971430.226   115.6 1429.42  123.491430.192   125.1 1430.35   134.5 1432.01
   153.4 1435.59   162.9 1437.55   191.2 1443.74   200.7 1446.27   210.2 1449.21
  244.741460.469   257.4 1464.81
#Mann= 4 ,-1 , 0
       0     .12       0  108.97    .045       0  123.49     .12       0
  244.74    .016       0
Bank Sta=108.97,123.49
XS Rating Curve= 0 ,0
Exp/Cntr=0.3,0.1

Type RM Length L Ch R = 1 ,978.8   ,88.3,82,75.6
XS GIS Cut Line= 4
     1792745.675      197980.389     1792673.627      198038.549
     1792622.411      198113.202     1792598.106       198212.16
#Sta/Elev= 28
       0 1451.56     9.3 1450.25    18.5 1448.57    27.8  1446.3    46.3  1439.9
    55.6 1437.31    64.8 1435.54    74.1 1434.21    83.3 1433.43    92.6 1432.95
   101.6  1432.3   110.7 1429.52   119.8 1426.39  125.341425.374   128.8 1424.74
   137.8 1425.05  139.94 1425.45   146.9 1426.75     165 1430.79   183.1 1434.68
   220.2 1442.97   229.4 1445.19   238.7 1447.81     248 1451.01   257.2 1454.71
   266.5  1458.6   275.8 1462.28     285 1465.76
#Mann= 3 ,-1 , 0
       0     .12       0  125.34    .045       0  139.94     .12       0
Bank Sta=125.34,139.94
XS Rating Curve= 0 ,0
Exp/Cntr=0.3,0.1

Type RM Length L Ch R = 1 ,896.8   ,43.7,43.7,43.7
XS GIS Cut Line= 4
     1792702.273       197895.32     1792604.706      197965.964
     1792563.927      198086.255      1792542.55      198195.667
#Sta/Elev= 30
       0 1454.37    27.8  1452.6    37.1 1451.85    46.3 1450.89    55.6 1449.69
    64.9 1448.28    74.1 1446.62    83.4 1444.57    92.7    1442   111.2 1433.41
   120.5 1430.11   130.2 1428.37     140 1427.29   149.8 1426.02   159.5 1424.59
   169.3 1423.51   179.1 1423.24  184.52  1423.5   188.8  1423.7   198.6 1424.74
   218.2  1427.7   227.9 1429.41   247.5 1433.16   256.8 1435.14   284.6 1441.73
   293.9 1444.09   303.2 1446.64   312.5 1449.47   321.8  1452.6     359 1465.97
#Mann= 3 ,-1 , 0
       0     .12       0   169.3    .045       0  184.52     .12       0
Bank Sta=169.3,184.52
XS Rating Curve= 0 ,0
Exp/Cntr=0.3,0.1

Type RM Length L Ch R = 1 ,853.1   ,101.7,98.4,95.2
XS GIS Cut Line= 4
      1792663.21      197879.695     1792565.643      197950.339
     1792524.865       198070.63     1792503.488      198180.042
#Sta/Elev= 30
       0 1456.21     9.3 1455.71    18.5 1454.91    27.8 1453.71    37.1  1452.3
    46.3 1450.63    55.6 1448.51    64.9 1445.77    74.1  1441.6   84.871435.295
    92.7 1430.42   101.9 1428.07   111.2 1427.24   120.5 1426.83   130.2 1426.03
     140 1425.02   159.5 1422.32   169.3 1422.01  174.171422.343   179.1 1422.68
  195.091424.505   227.9 1427.98   237.7 1429.25  249.171431.069   256.8 1432.57
     266 1434.81   275.3 1437.38   303.2 1445.76   321.8 1451.12     359 1461.11
#Mann= 6 ,-1 , 0
       0     .12       0   84.87    .016       0   159.5    .045       0
  174.17     .12       0  195.09    .016       0  249.17     .12       0
Bank Sta=159.5,174.17
XS Rating Curve= 0 ,0
Exp/Cntr=0.3,0.1

Type RM Length L Ch R = 1 ,754.7   ,108.2,104.9,101.5
XS GIS Cut Line= 4
      1792506.96      197831.952     1792469.634      197910.945
     1792450.536      198016.848     1792466.161       198145.32
#Sta/Elev= 30
       0 1445.99     9.7 1445.94    19.4  1445.4    29.1 1444.11    38.8 1441.92
    48.5 1438.28      68 1430.05   77.651426.379    87.4 1423.35    97.2 1421.34
   106.9 1420.28   113.51419.761   123.3 1419.21   126.5 1419.06   136.3 1419.28
   165.6 1421.74     195 1423.44   204.2  1424.4   213.5  1425.6   222.7 1426.97
     232  1428.5   241.61430.269   250.4 1432.01   259.7 1434.02   268.9 1436.34
   278.2 1439.15  283.121440.904   305.9 1449.23   315.2 1452.14   324.4 1454.53
#Mann= 7 ,-1 , 0
       0     .12       0   77.65    .016       0   113.5     .12       0
   123.3    .045       0   136.3     .12       0   241.6    .016       0
  283.12     .12       0
Bank Sta=123.3,136.3
XS Rating Curve= 0 ,0
Exp/Cntr=0.3,0.1

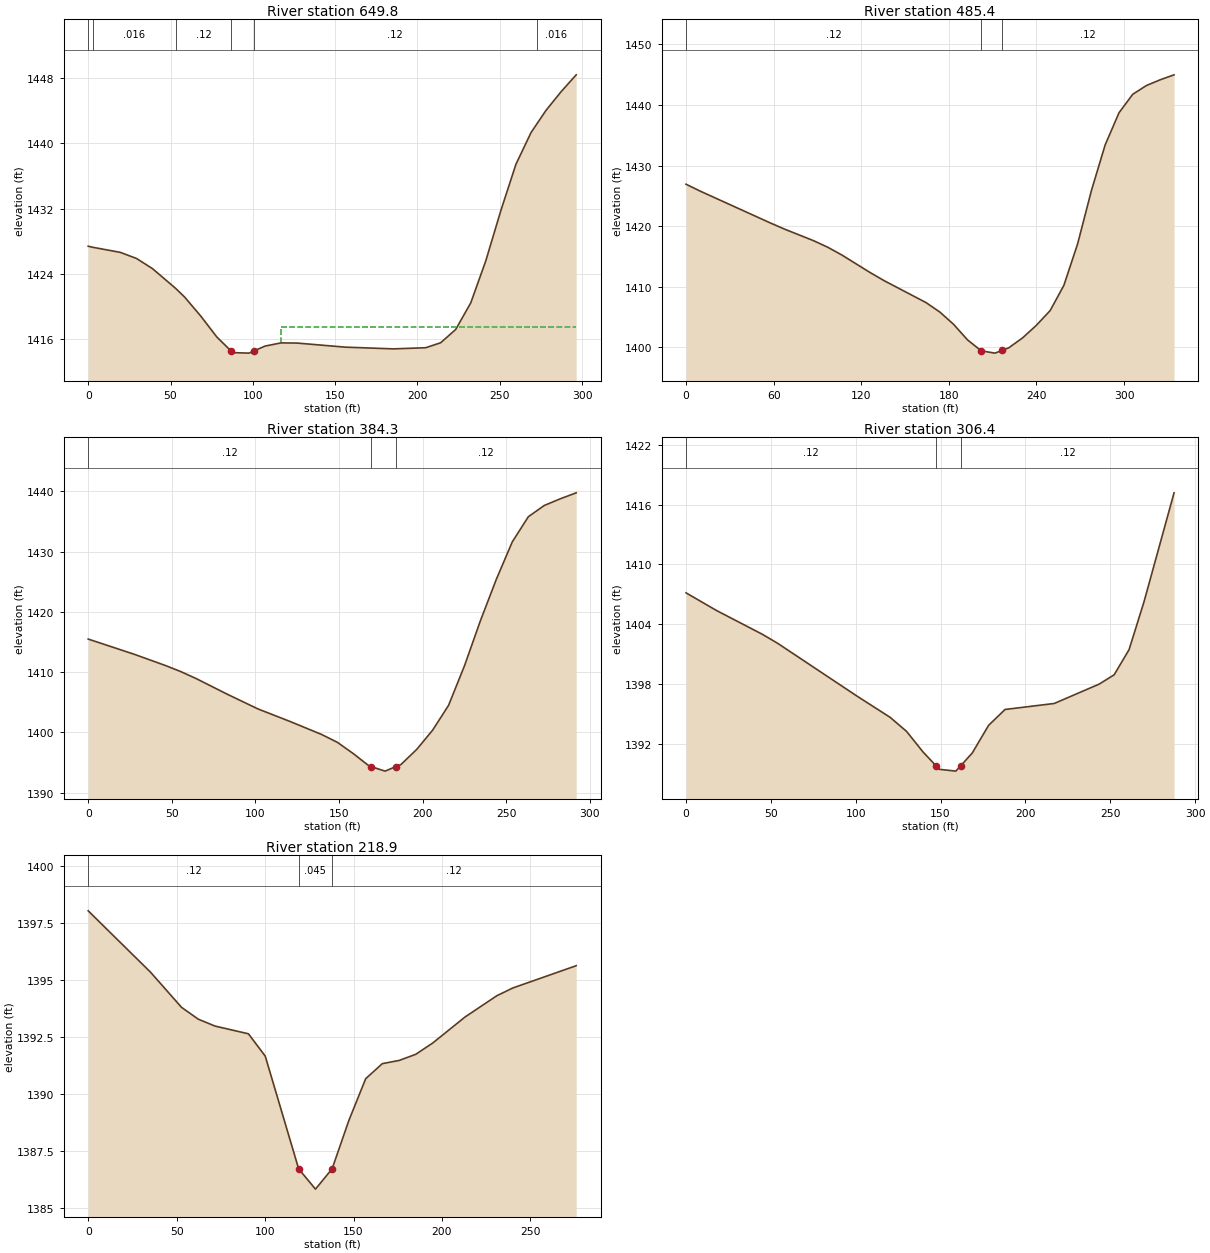
Type RM Length L Ch R = 1 ,649.8   ,180.1,164.4,148.6
XS GIS Cut Line= 3
     1792361.127      197845.841      1792355.05      198050.702
     1792374.148      198140.112
#Sta/Elev= 30
       0  1427.4    2.641427.279    19.5 1426.65    29.3 1425.91      39 1424.67
   53.131422.246    58.6 1421.18    68.3 1418.88    78.1 1416.31   86.811414.588
    87.8 1414.39    97.6 1414.33   100.5 1414.58   107.4 1415.19   117.1 1415.58
   126.9 1415.56   156.2 1415.06   185.4 1414.85     205 1414.99   214.1  1415.6
   223.2 1417.22   232.4 1420.49   241.5 1425.62   250.7  1431.8   259.8 1437.42
     269 1441.31  272.471442.343   278.1 1444.02   287.2 1446.29   296.4 1448.36
#Mann= 6 ,-1 , 0
       0     .12       0    2.64    .016       0   53.13     .12       0
   86.81    .045       0   100.5     .12       0  272.47    .016       0
#XS Ineff= 2 , 0
                          117.03         1417.57
Permanent Ineff=
       F       F
Bank Sta=86.81,100.5
XS Rating Curve= 0 ,0
Exp/Cntr=0.3,0.1

Type RM Length L Ch R = 1 ,485.4   ,95.2,101.1,107
XS GIS Cut Line= 3
     1792240.467      197857.125     1792210.085      197999.487
     1792325.536      198148.792
#Sta/Elev= 29
       0 1426.93     9.7 1425.79    58.2 1420.49    67.9 1419.48    87.3 1417.62
      97 1416.54   106.8 1415.24   126.2 1412.34   135.9 1410.99   164.4  1407.4
   173.9 1405.83   183.3 1403.81   192.8 1401.25   202.2 1399.44   211.6 1399.06
  216.321399.498   221.1 1399.94   230.5 1401.57   239.9 1403.63   249.4 1406.07
   258.8 1410.23   268.2 1417.05   277.7 1425.89   287.1 1433.41   296.6 1438.72
     306 1441.77   315.4 1443.22   324.9 1444.17   334.3 1444.98
#Mann= 3 ,-1 , 0
       0     .12       0   202.2    .045       0  216.32     .12       0
Bank Sta=202.2,216.32
XS Rating Curve= 0 ,0
Exp/Cntr=0.3,0.1

Type RM Length L Ch R = 1 ,384.3   ,75.1,77.9,80.8
XS GIS Cut Line= 4
     1792157.134      197937.855     1792138.905      198037.681
     1792183.175      198142.716     1792246.543       198185.25
#Sta/Elev= 27
       0 1415.48    27.7 1412.94    46.1  1411.1    55.4 1410.08    64.6 1408.92
      83 1406.35   101.5 1403.89   120.5 1401.83   139.5 1399.66     149 1398.35
   158.5 1396.48     168 1394.42     169 1394.33   177.5 1393.57     184 1394.32
     187 1394.66   196.5 1397.19     206 1400.38   215.5 1404.49     225 1411.04
   234.5  1418.5   244.1 1425.43   253.6 1431.61   263.2 1435.78   272.7 1437.64
   282.2 1438.74   291.8 1439.74
#Mann= 3 ,-1 , 0
       0     .12       0     169    .045       0     184     .12       0
Bank Sta=169,184
XS Rating Curve= 0 ,0
Exp/Cntr=0.3,0.1

Type RM Length L Ch R = 1 ,306.4   ,85.7,87.5,89.2
XS GIS Cut Line= 4
     1792093.766      197983.862     1792072.064      198052.438
     1792111.127      198192.195     1792179.703      198208.688
#Sta/Elev= 21
       0 1407.16      18 1405.39      45 1403.01      54 1402.11     101  1396.8
   120.3  1394.7     130 1393.29   139.6 1391.25  147.231389.871   149.3  1389.5
     159 1389.32     1621389.881   168.7 1391.14   178.3  1393.9     188 1395.49
     217 1396.09   243.5 1398.03   252.3 1398.96   261.1 1401.48   269.9 1406.27
   287.6 1417.17
#Mann= 3 ,-1 , 0
       0     .12       0  147.23    .045       0     162     .12       0
Bank Sta=147.23,162
XS Rating Curve= 0 ,0
Exp/Cntr=0.3,0.1

Type RM Length L Ch R = 1 ,218.9   ,220.1,218.9,217.7
XS GIS Cut Line= 4
     1792019.113      198038.549     1791996.543      198086.292
     1792026.057       198234.73     1792097.238       198243.41
#Sta/Elev= 20
       0 1398.03    35.2 1395.34    52.8 1393.79    62.3 1393.27    71.7 1392.97
    90.6 1392.63   100.1 1391.65     119  1386.7   128.5 1385.81   137.9  1386.7
   147.4 1388.83   156.9 1390.66   166.3 1391.32   175.8 1391.46   185.2 1391.73
   194.7 1392.22   213.1 1393.37     231  1394.3     240 1394.64   275.9 1395.62
#Mann= 3 ,-1 , 0
       0     .12       0     119    .045       0   137.9     .12       0
Bank Sta=119,137.9
XS Rating Curve= 0 ,0
Exp/Cntr=0.3,0.1

Chan Stop Cuts=-1
Use User Specified Reach Order=0
Composite Channel Slope=5